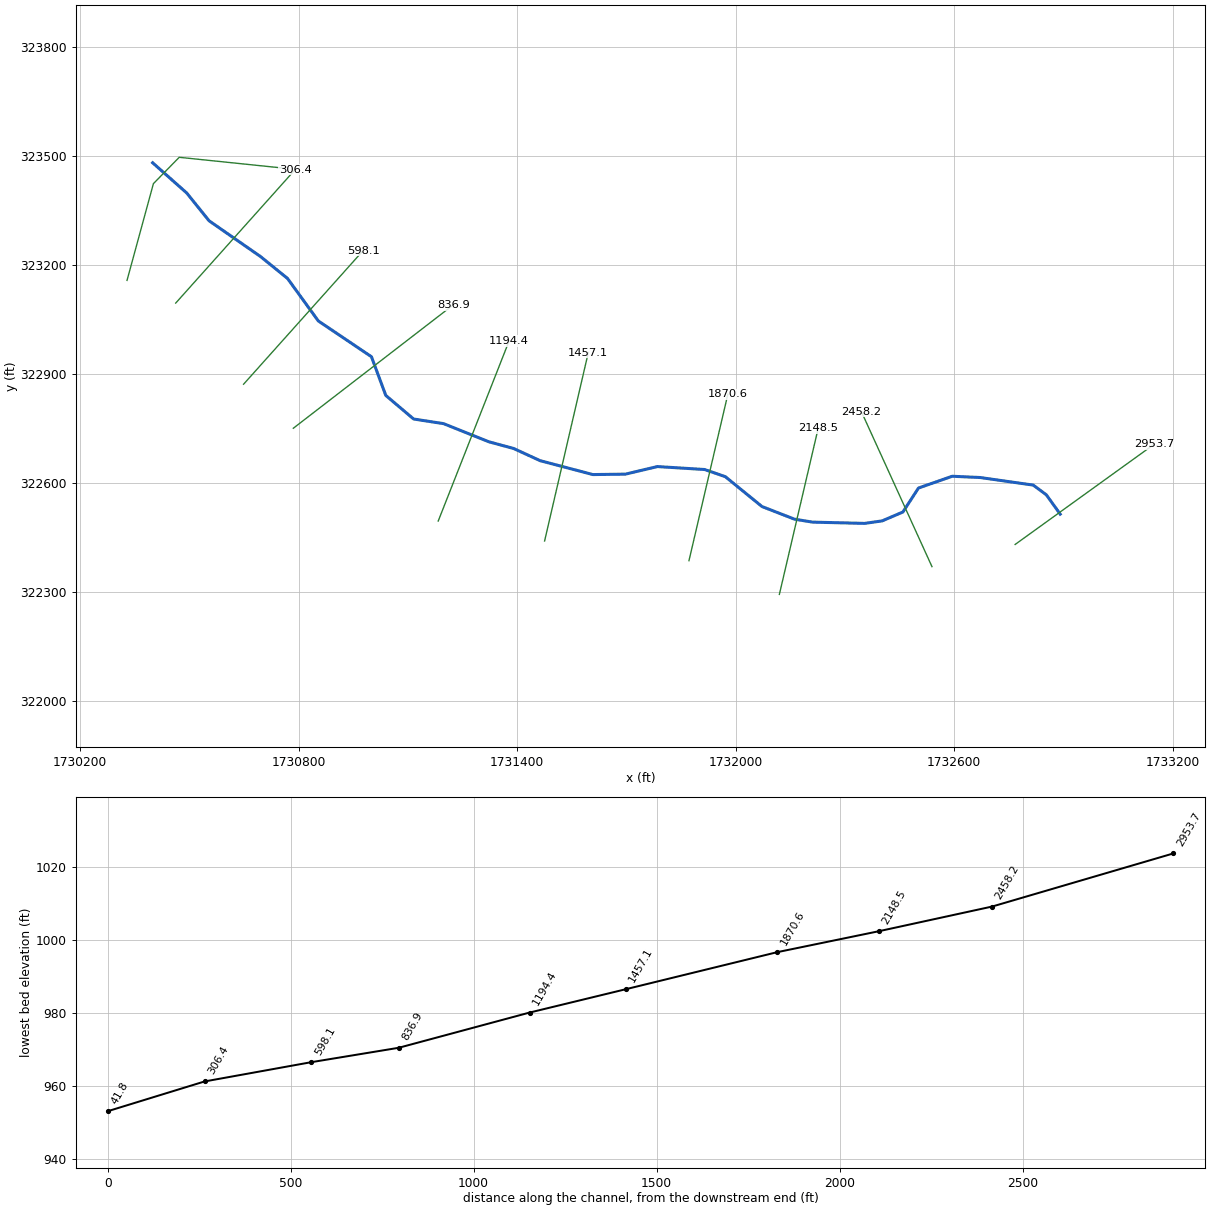
--- PIGEONRTBR.prj (project) ---

Proj Title=PIGEONRTBR
Current Plan=p01
Default Exp/Contr=0,0
English Units
Geom File=g01
Flow File=f01
Plan File=p01
BEGIN DESCRIPTION:
END DESCRIPTION:
DSS Export Rating Curves= 0
DSS Export Rating Curve Sorted= 0
DSS Export Volume Flow Curves= 0
DXF OffsetX= 0
DXF OffsetY= 0
DXF ScaleX= 0
DXF ScaleY= 0

--- PIGEONRTBR.p01 (plan) ---

Plan Title=Floodplain
Program Version=4.00
Geom File=g01
Flow File=f01
K Sum by GR=0
Std Step Tol=0.01
Critical Tol=0.01
Num of Std Step Trials=20
Max Error Tol=0.3
Flow Tol Ratio=0.001
Split Flow NTrial=30
Split Flow Tol=0.02
Split Flow Ratio=0.02
Log Output Level=0
Friction Slope Method=1
Unsteady Friction Slope Method=2
Unsteady Bridges Friction Slope Method=1
Global Log Level=0
CheckData=False
Run HTab=0
Run UNet=0
Run PostProcess=0
UNET Theta=0
UNET Theta Warmup=0
UNET ZTol=0
UNET ZSATol=0
UNET MxIter=0
UNET MaxInSteps=0
UNET DtIC=0
UNET DtMin=0
UNET MaxCRTS=0
UNET WFStab=0
UNET SFStab=0
UNET WFX=0
UNET SFX=0
UNET DSS MLevel=0
UNET DZMax Abort=0
UNET Convert EG Bridges=0
UNET Use Existing IB Tables=0
UNET Froude Limit=0
UNET Froude Power=0
Write IC File=0
Echo Input=False
Echo Output=False
Write Detailed=0

--- PIGEONRTBR.f01 (steady flow) ---

Flow Title=NFF Regression Equation
Program Version=4.00
Number of Profiles=1
Profile Names=P100yr
River Rch & RM=PIGEONRTBR,Main      ,2953.7
915.4482
River Rch & RM=PIGEONRTBR,Main      ,41.8
973.6084
Boundary for River Rch & Prof#=PIGEONRTBR,Main      ,1
Up Type=0
Dn Type=3
Dn Slope=0.022057

--- PIGEONRTBR.g01 (geometry) ---

Geom Title=USGS 10m DEM
Program Version=4.10

River Reach=PIGEONRTBR      ,Main
Reach XY= 30
     1732890.879      322513.751     1732852.659      322567.028
     1732816.754      322593.667     1732670.821      322614.515
     1732594.379       322617.99     1732501.723       322585.56
     1732458.869      322519.542     1732402.117       322495.22
     1732353.473      322488.271     1732211.014      322491.745
     1732161.211      322499.853     1732072.029      322534.599
     1731971.266      322616.831     1731914.514      322636.521
     1731784.795      322644.628     1731696.772      322623.781
      1731607.59      322622.622     1731462.815      322660.843
     1731389.848      322694.431     1731321.514      322712.962
     1731197.586      322762.765     1731115.354      322775.505
     1731038.912      322840.364     1730999.533      322946.919
       1730853.6      323045.366     1730769.051      323162.345
     1730694.926      323222.571     1730553.625      323321.019
      1730492.24       323397.46     1730398.668      323480.687

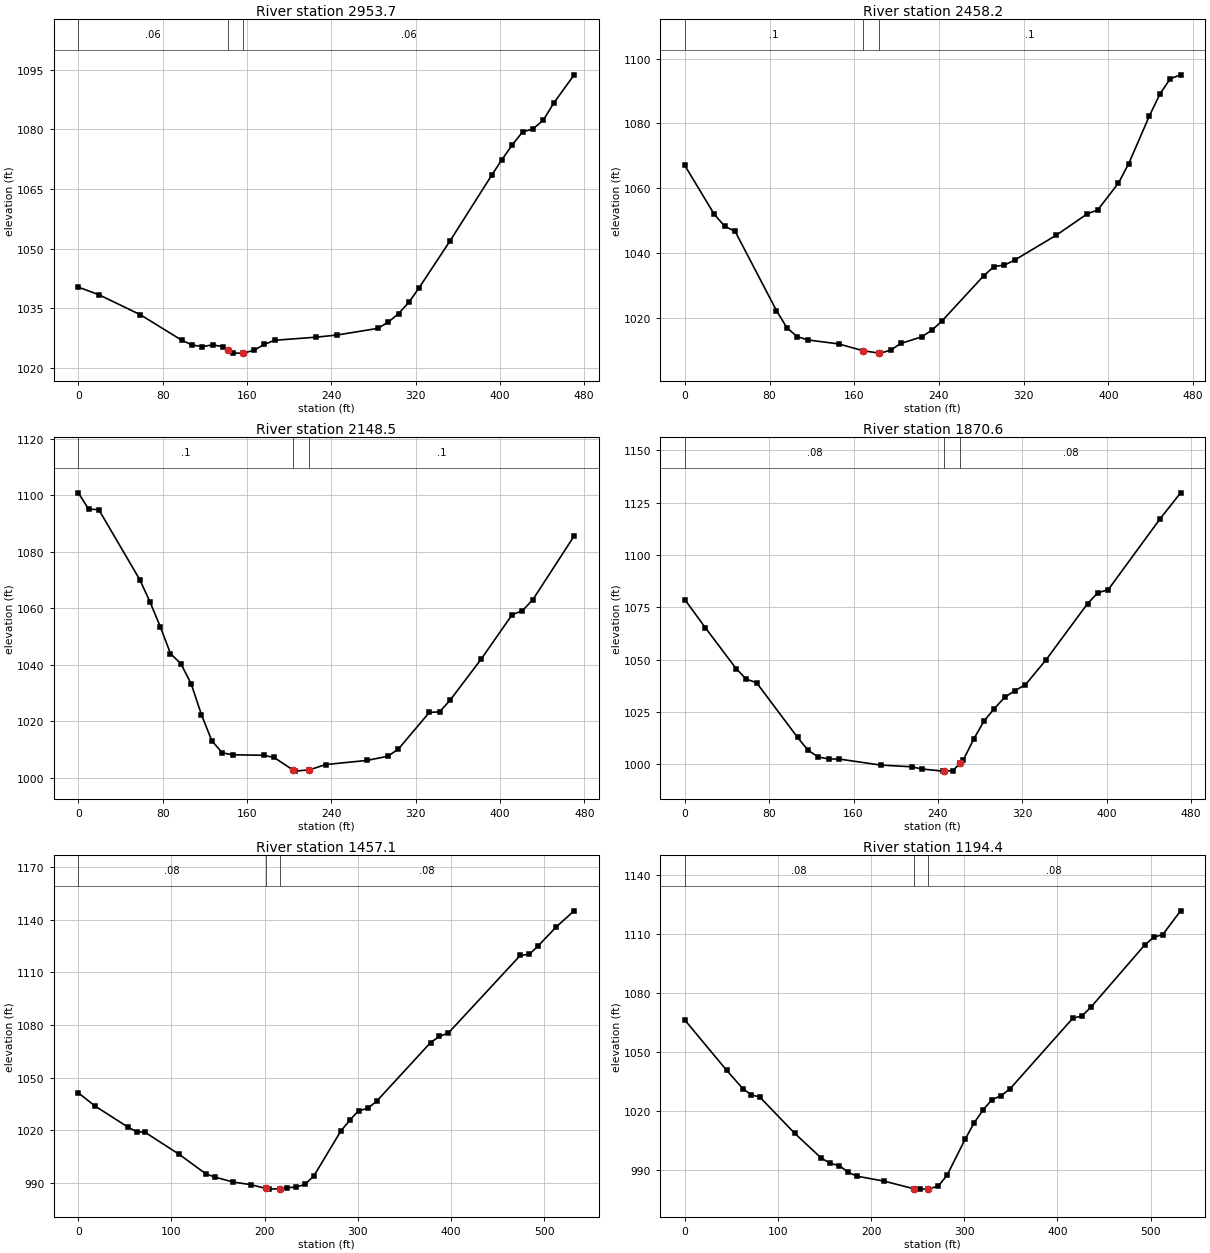
Type RM Length L Ch R = 1 ,2953.7  ,464.5,495.4,526.4
XS GIS Cut Line= 2
      1732767.18      322430.343      1733148.59      322705.862
#Sta/Elev= 30
       0 1040.34    19.6 1038.42    58.8 1033.41      98    1027   107.8 1025.82
   117.6 1025.35   127.4 1025.82   137.2 1025.36   141.6 1024.64     147 1023.74
   156.6 1023.74   166.6 1024.45   176.4 1025.92   186.2 1026.97   225.5 1027.75
   245.1 1028.28   284.3 1029.97   294.1 1031.54   303.9  1033.7   313.7 1036.54
   323.5 1040.23   352.9 1052.04   392.1 1068.44   401.9 1072.39   411.7 1076.11
   421.5 1079.36   431.3 1080.14   441.1 1082.29   450.9 1086.56   470.5 1093.75
#Mann= 3 , 0 , 0
       0     .06       0   141.6    .045       0   156.6     .06       0
Bank Sta=141.6,156.6
XS Rating Curve= 0 ,0
Exp/Cntr=0.3,0.1

Type RM Length L Ch R = 1 ,2458.2  ,323.5,309.7,296
XS GIS Cut Line= 3
     1732538.705      322369.332     1732527.168      322394.722
     1732344.991      322795.658
#Sta/Elev= 30
       0 1067.04    27.9 1051.95    37.7 1048.28    47.5 1046.74    86.6  1022.3
    96.4    1017   106.2 1014.29     116 1013.26   145.3 1012.03   168.4 1009.93
   183.4  1009.2   184.5 1009.19   194.3 1010.08     204 1012.16   223.6 1014.19
   233.4 1016.26   243.2  1019.2   282.3 1033.04   292.1 1035.89   301.9 1036.32
   311.7  1037.9   350.8 1045.53   380.2 1052.14     390 1053.32   409.6 1061.62
   419.3 1067.62   438.9  1082.4   448.7 1089.02   458.5 1093.78   468.3 1094.98
#Mann= 3 , 0 , 0
       0      .1       0   168.4    .045       0   183.4      .1       0
Bank Sta=168.4,183.4
XS Rating Curve= 0 ,0
Exp/Cntr=0.3,0.1

Type RM Length L Ch R = 1 ,2148.5  ,277.9,277.9,277.9
XS GIS Cut Line= 3
     1732119.669      322292.842     1732139.513      322377.946
      1732226.45      322750.799
#Sta/Elev= 30
       0 1100.94     9.7 1095.19    19.4 1094.98    58.3 1070.19      68 1062.28
    77.7 1053.57    87.4 1044.03    97.2 1040.47     107 1033.34   116.8 1022.36
   126.6 1013.17   136.5  1008.9   146.3 1008.22   175.7 1008.04   185.6 1007.28
     204 1002.71   205.2 1002.43     219 1002.88   234.6 1004.75   273.9 1006.23
   293.5  1007.7   303.4  1010.2   332.8  1023.2   342.6 1023.42   352.4 1027.47
   381.9 1042.01   411.3 1057.76   421.2 1059.25     431 1063.11   470.2 1085.67
#Mann= 3 , 0 , 0
       0      .1       0     204    .045       0     219      .1       0
Bank Sta=204,219
XS Rating Curve= 0 ,0
Exp/Cntr=0.3,0.1

Type RM Length L Ch R = 1 ,1870.6  ,413.2,413.5,413.7
XS GIS Cut Line= 3
     1731871.446      322385.631      1731891.29      322470.735
     1731978.227      322843.588
#Sta/Elev= 30
       0 1078.66    19.4 1065.26    48.6 1045.72    58.3  1040.6      68 1038.96
     107 1012.76   116.8  1006.7   126.6 1003.42   136.5 1002.51   146.3 1002.47
   185.6  999.58     215  998.77   224.8  997.72   244.5  996.69   246.1  996.73
   254.3  996.92   261.1 1000.45   264.1    1002   273.9  1011.9   283.7 1020.59
   293.5 1026.54   303.4 1032.01   313.2 1035.21     323 1037.94   342.6 1049.88
   381.9 1076.69   391.7  1081.9   401.5 1083.35   450.6 1117.15   470.2 1129.65
#Mann= 3 , 0 , 0
       0     .08       0   246.1    .045       0   261.1     .08       0
Bank Sta=246.1,261.1
XS Rating Curve= 0 ,0
Exp/Cntr=0.3,0.1

Type RM Length L Ch R = 1 ,1457.1  ,266,262.7,259.4
XS GIS Cut Line= 3
     1731474.992      322439.881       1731497.2      322535.816
     1731595.041      322958.479
#Sta/Elev= 30
       0 1041.36    17.9 1033.87    53.7 1021.71    62.7  1019.2    71.6 1018.91
   108.1 1006.42     137  995.22   146.7   993.4     166   990.6   185.2  989.09
   201.3  986.93   204.5  986.55   216.3  986.77   223.8  987.44   233.4  987.64
   243.1  989.19   252.7  993.92   281.6 1019.42   291.3 1025.74   300.9 1031.21
   310.6 1032.49   320.2 1036.57   378.1 1069.97   387.7 1073.52   397.3 1075.45
   474.5 1119.64   484.1 1120.21   493.8 1125.07     513 1135.81   532.3 1144.99
#Mann= 3 , 0 , 0
       0     .08       0   201.3    .045       0   216.3     .08       0
Bank Sta=201.3,216.3
XS Rating Curve= 0 ,0
Exp/Cntr=0.3,0.1

Type RM Length L Ch R = 1 ,1194.4  ,369.7,357.5,345.1
XS GIS Cut Line= 3
     1731182.928      322494.805     1731218.922      322586.463
     1731377.505       322990.28
#Sta/Elev= 30
       0 1066.22    44.8 1040.68    62.7 1031.08    71.6 1028.11    80.6 1026.97
   117.8 1008.64   146.7  995.86   156.3  993.29     166  992.07   175.6  988.66
   185.2  986.71   214.2  984.21   245.8  980.36   252.7  980.16   260.8  980.22
     272  981.63   281.6  987.25   300.9 1005.47   310.6 1013.87   320.2 1020.41
   329.8 1025.69   339.5 1027.65   349.1 1031.16   416.6 1067.14   426.3 1068.24
   435.9 1072.68   493.8 1104.42   503.4 1108.35     513 1109.63   532.3 1121.76
#Mann= 3 , 0 , 0
       0     .08       0   245.8    .045       0   260.8     .08       0
Bank Sta=245.8,260.8
XS Rating Curve= 0 ,0
Exp/Cntr=0.3,0.1

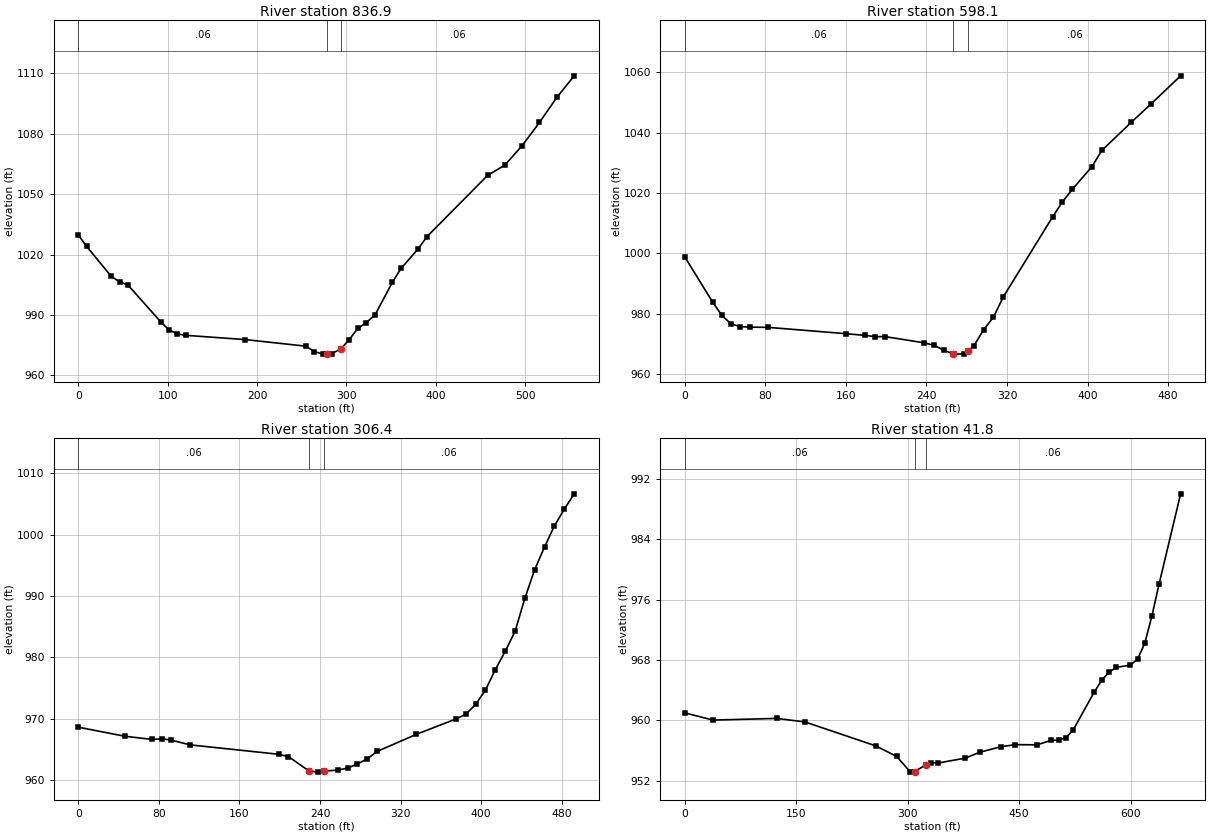
Type RM Length L Ch R = 1 ,836.9   ,234.7,238.8,243.1
XS GIS Cut Line= 3
        1730785.      322750.101      1730894.51      322834.752
     1731224.005      323089.451
#Sta/Elev= 30
       0 1029.77     9.2 1024.07    36.9 1009.16    46.1 1006.41    55.4 1004.93
    92.3  986.52   101.5  982.57   110.7  980.55     120  979.87   186.8  977.75
   254.6  974.47   264.3  971.75     274  970.52   278.7  970.67   283.7  970.82
   293.7  973.07   303.1  977.69   312.8   983.3   322.4   986.2   332.1  990.07
   351.5 1006.27   361.2 1013.09   380.5 1022.95   390.2  1028.9     458 1059.32
   477.4 1064.46   496.8 1074.18   516.1 1085.66   535.5 1098.08   554.9 1108.81
#Mann= 3 , 0 , 0
       0     .06       0   278.7    .045       0   293.7     .06       0
Bank Sta=278.7,293.7
XS Rating Curve= 0 ,0
Exp/Cntr=0.3,0.1

Type RM Length L Ch R = 1 ,598.1   ,291.7,291.6,291.6
XS GIS Cut Line= 3
     1730648.456      322871.279     1730715.775      322946.686
     1730976.344       323238.56
#Sta/Elev= 30
       0  998.79    27.6  983.83    36.8  979.43      46  976.58    55.1  975.72
    64.3  975.51    82.7  975.45   159.8  973.36   179.3  972.78   189.1  972.37
   198.9  972.38     238  970.31   247.8  969.47   257.6  967.83   266.4  966.71
   267.4  966.58   277.2  966.64   281.4  967.74   286.9  969.18   296.7  974.65
   306.5  978.82   316.3  985.53   365.2 1012.02     375 1017.02   384.8 1021.15
   404.3  1028.7   414.1 1034.05   443.4 1043.39     463 1049.47   492.4 1058.79
#Mann= 3 , 0 , 0
       0     .06       0   266.4    .045       0   281.4     .06       0
Bank Sta=266.4,281.4
XS Rating Curve= 0 ,0
Exp/Cntr=0.3,0.1

Type RM Length L Ch R = 1 ,306.4   ,265.7,264.7,263.7
XS GIS Cut Line= 3
     1730462.119      323094.579     1730529.438      323169.986
     1730790.007       323461.86
#Sta/Elev= 30
       0  968.62      46  967.15    73.5  966.62    82.7  966.74    91.9  966.53
   110.9  965.74   198.9  964.21   208.7  963.83   229.1  961.48     238   961.3
   244.1  961.46   257.6  961.64   267.4  961.95   277.2  962.64   286.9  963.46
   296.7  964.67   335.8  967.46     375  969.96   384.8  970.73   394.5  972.32
   404.3  974.65   414.1     978   423.9  980.96   433.7  984.22   443.4   989.6
   453.2  994.28     463  997.98   472.8 1001.42   482.6 1004.13   492.4 1006.63
#Mann= 3 , 0 , 0
       0     .06       0   229.1    .045       0   244.1     .06       0
Bank Sta=229.1,244.1
XS Rating Curve= 0 ,0
Exp/Cntr=0.3,0.1

Type RM Length L Ch R = 1 ,41.8    ,41.5,41.8,42
XS GIS Cut Line= 4
     1730328.325      323156.948     1730400.802      323423.223
     1730471.704      323495.701     1730760.038      323465.764
#Sta/Elev= 30
       0  960.99    38.1  960.04   123.7  960.26   161.8  959.79   256.9  956.63
   285.2  955.22   303.6  953.15   309.4  953.23   324.4  954.12   331.3  954.41
   340.5  954.35   377.4     955   396.7  955.78   425.7  956.52     445  956.79
     474  956.76   493.3  957.37     503  957.39   512.6   957.7   522.3  958.68
   551.3  963.81     561   965.3   570.6  966.35   580.3  967.01   599.6  967.32
   609.3  968.12   618.9   970.2   628.6  973.84   638.2  978.05   667.2  989.99
#Mann= 3 , 0 , 0
       0     .06       0   309.4    .045       0   324.4     .06       0
Bank Sta=309.4,324.4
XS Rating Curve= 0 ,0
Exp/Cntr=0.3,0.1

Chan Stop Cuts=-1
Use User Specified Reach Order=0
Composite Channel Slope=5